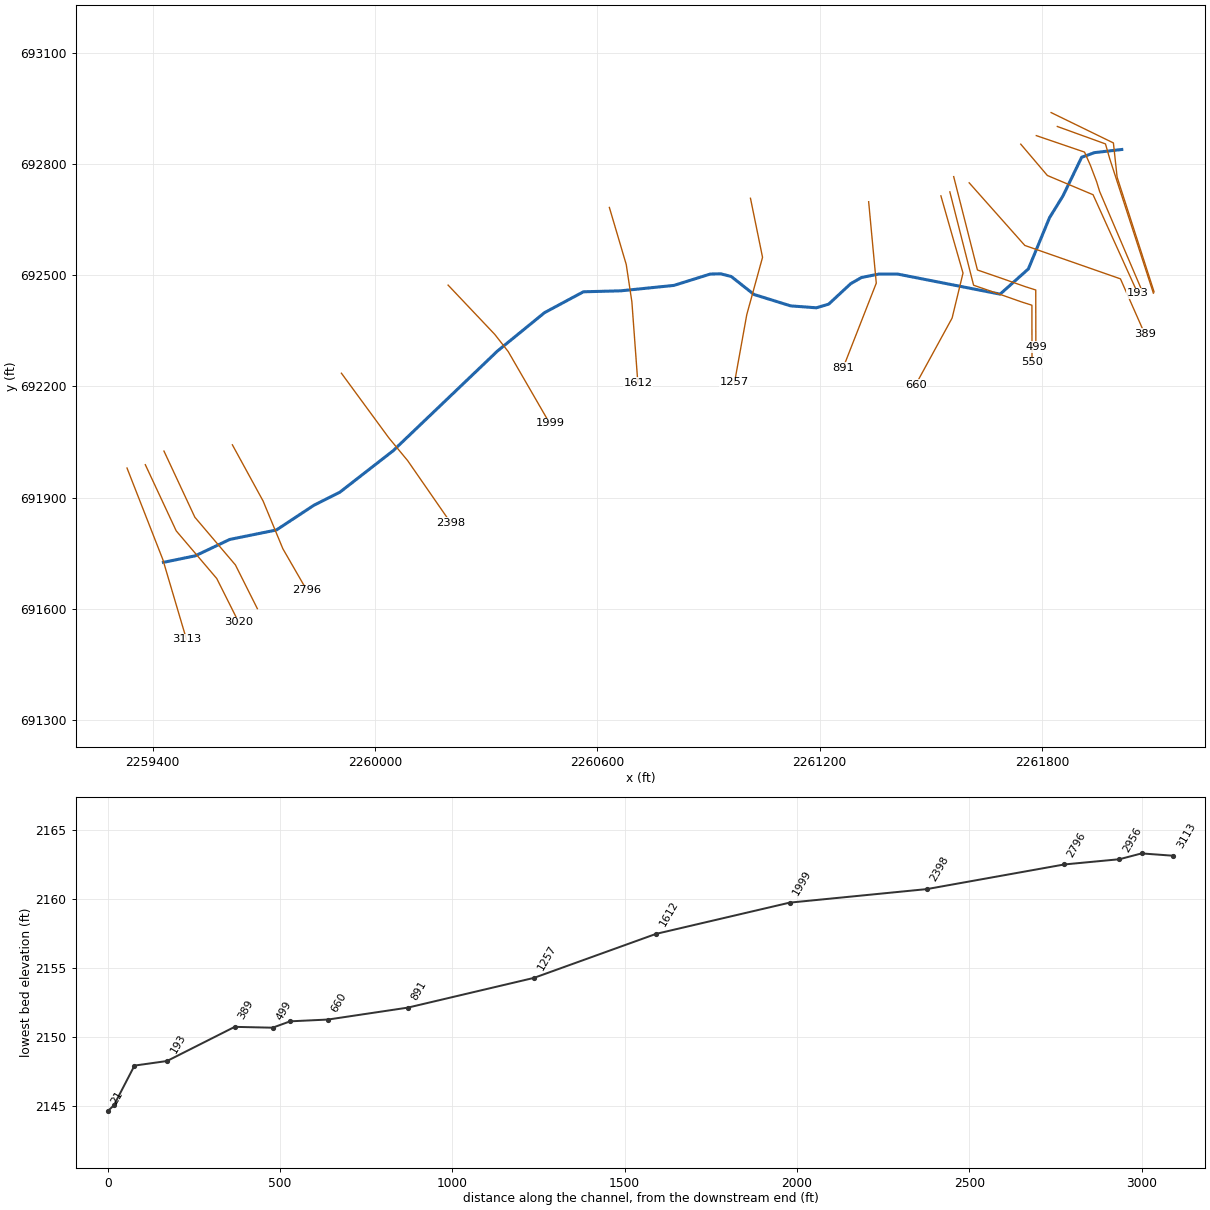
--- ROARCKT3.prj (project) ---

Proj Title=ROARCKT3
Current Plan=p01
Default Exp/Contr=0,0
English Units
Geom File=g01
Flow File=f01
Plan File=p01
BEGIN DESCRIPTION:
----------MODEL BY WOOD PLC 2022----------
AFH study
Randolph County, WV
HEC-RAS Version: RAS 6.2
Vertical Datum: NAVD88
Projection: NAD 1983 StatePlane West Virginia S FIPS 4702 (US Feet)
Terrain: 1-meter LIDAR (FEMA Region III 3DEP collected 2016-2018)
Land Use: 2019 NLCD
Hydrologic Method:
WV SIR2010-5033 regression equations
Additional Model Notes:
None
END DESCRIPTION:
DSS Export Rating Curves= 0
DSS Export Rating Curve Sorted= 0
DSS Export Volume Flow Curves= 0
DXF OffsetX= 0
DXF OffsetY= 0
DXF ScaleX= 0
DXF ScaleY= 0

--- ROARCKT3.p01 (plan) ---

Plan Title=Floodplain
Program Version=6.20
Short Identifier=Floodplain
Geom File=g01
Flow File=f01
Subcritical Flow
K Sum by GR= 0
Std Step Tol= 0.01
Critical Tol= 0.01
Num of Std Step Trials= 20
Max Error Tol= 0.3
Flow Tol Ratio= 0.001
Split Flow NTrial= 30
Split Flow Tol= 0.02
Split Flow Ratio= 0.02
Log Output Level= 0
Friction Slope Method= 1
Unsteady Friction Slope Method= 2
Unsteady Bridges Friction Slope Method= 1
Parabolic Critical Depth
Global Vel Dist= 0 , 0 , 0
Global Log Level= 0
CheckData=True
Encroach Param=-1 ,0,0, 0
Mapping Interval=1HOUR
Computation Time Step Use Courant=        0
Computation Time Step Use Time Series=    0
Computation Time Step Count To Double=0
Computation Time Step Max Doubling=0
Computation Time Step Max Halving=0
Computation Time Step Residence Courant=0
Run HTab= 0
Run UNet= 0
Run Sediment= 0
Run PostProcess= 0
Run WQNet= 0
Run RASMapper=-1
UNET Theta= 0
UNET Theta Warmup= 0
UNET ZTol= 0
UNET ZSATol= 0
UNET MxIter= 0
UNET Max Iter WO Improvement= 0
UNET MaxInSteps= 0
UNET DtIC= 0
UNET DtMin= 0
UNET MaxCRTS= 0
UNET WFStab= 0
UNET SFStab= 0
UNET WFX= 1
UNET SFX= 1
UNET Gravity=32.174
UNET 1D Methodology=Finite Difference
UNET DSS MLevel= 1
UNET Pardiso=0
UNET DZMax Abort= 0
UNET Use Existing IB Tables= 0
UNET Froude Reduction=False
UNET Froude Limit= 0
UNET Froude Power= 0
UNET D1 Cores= 0
UNET WindReference=Eulerian
UNET WindDragFormulation=Hsu (1988)
UNET D2 Coriolis=0
UNET D2 Cores= 0
UNET D2 Theta= 1
UNET D2 Theta Warmup= 1
UNET D2 Z Tol= 0.01
UNET D2 Volume Tol= 0.01
UNET D2 Max Iterations= 20
UNET D2 Equation= 0
UNET D2 RampUpFraction=0.1
UNET D2 TimeSlices= 1
UNET D2 Turbulence Formulation=Non-Conservative (original)
UNET D2 Eddy Viscosity=0.3
UNET D2 Transverse Eddy Viscosity=0.1
UNET D2 Smagorinsky Mixing=0
UNET D2 BCVolumeCheck=0
UNET D2 Cores=0
UNET D2 SolverType=PARDISO (Direct)
UNET D2 Minimum Iterations= 2147483647
UNET D2 Maximum Iterations= 2147483647
UNET D2 Restart Number= 10
UNET D2 Relaxation Coeff=1.3
UNET D2 SOR Precondition Iterations= 10
UNET D2 ILUT Maximum Fill= 8
UNET D2 ILUT Tolerance=1E-08
UNET D1D2 MaxIter= 0
UNET D1D2 ZTol=0.01
UNET D1D2 QTol=0.1
UNET D1D2 MinQTol=1
Write IC File= 0
Write IC File at Fixed DateTime=0
Write IC File at Sim End=0
Echo Input=False
Echo Parameters=False
Echo Output=False
Write Detailed= 0
HDF Write Warmup=0
HDF Write Time Slices=0
HDF Flush=0
HDF Compression= 1
HDF Chunk Size= 1
HDF Spatial Parts= 1
HDF Use Max Rows=0
HDF Fixed Rows= 1
Calibration Method= 0
Calibration Iterations= 20
Calibration Max Change=0.05
Calibration Tolerance=0.2
Calibration Maximum=1.5
Calibration Minimum=0.5
Calibration Optimization Method= 1
WQ AD Non Conservative
WQ ULTIMATE=-1
WQ Max Comp Step=1HOUR
WQ Output Interval=15MIN
WQ Output Selected Increments= 0
WQ Output face flow=0
WQ Output face velocity=0
WQ Output face area=0
WQ Output face dispersion=0
WQ Output cell volume=0
WQ Output cell surface area=0
WQ Output cell continuity=0
WQ Output cumulative cell continuity=0
WQ Output face conc=0
WQ Output face dconc_dx=0
WQ Output face courant=0
WQ Output face peclet=0
WQ Output face adv mass=0
WQ Output face disp mass=0
WQ Output cell mass=0
WQ Output cell source sink temp=0
WQ Output nsm pathways=0
WQ Output nsm derived pathways=0
WQ Create Restart=0
WQ Fixed Restart=0
WQ System Summary=0
WQ Write To DSS=0
Sorting and Armoring Iterations= 10
XS Update Threshold= 0.02
Bed Roughness Predictor= 0
Hydraulics Update Threshold= 0.02
Energy Slope Method= 1
Volume Change Method= 1
Sediment Retention Method= 0
Sediment TS Multiplier= 1
Warm Up Method= 0
XS Weighting Method= 0
Number of US Weighted Cross Sections= 1
Number of DS Weighted Cross Sections= 1
Upstream XS Weight=0
Main XS Weight=1
Downstream XS Weight=0
Number of DS XS's Weighted with US Boundary= 1
Upstream Boundary Weight= 1
Weight of XSs Associated with US Boundary= 0
Number of US XS's Weighted with DS Boundary= 1
Downstream Boundary Weight= 0.5
Weight of XSs Associated with DS Boundary= 0.5
Percentile Method= 0
Sediment Output Level= 3
Mass or Volume Output= 0
Output Increment Type= 1
Profile and TS Output Increment= 1
Transport Output Increment 1
XS Output Flag= 0
XS Output Increment= 10
Read HDF5 Sediment Hotstart= 0
Sediment Hotstart Type= 0
Write Gradation File= 0
Read Gradation Hotstart= 0
Write HDF5 File= 1
Write Binary Output= 1
Write DSS Sediment File= 0
DSS Sediment Output Type= 1
SV Curve= 0
Specific Gage Flag= 0
Subcell Erosion Methods= 0
Subcell Deposition Methods= 0
Advection Scheme= 1
Matrix Solver= 0
Implicit Weighting Factor= 1
Maximum Outer Loop Convergence Iterations= 5
Convergence Maximum Absolute= 0.001
Convergence RMSE= 0.0001
Grain Fractions Max Abs Error= 0.001
Max Subgrid Regions= 1
Max Subgrid Length Scale= 3.402823E+38
Initial Layer Thickness= 3.402823E+38
Min Layer Thickness= 3.402823E+38
Max Layer Thickness= 3.402823E+38
Number of Layers= 5

--- ROARCKT3.f01 (steady flow) ---

Flow Title=Flow
Program Version=6.20
Number of Profiles= 1
Profile Names=P100yr
River Rch & RM=ROARCKT3,Main,3113
     375
Boundary for River Rch & Prof#=ROARCKT3,Main            , 1
Up Type= 0
Dn Type= 3
Dn Slope=0.02367
DSS Import GetInterval= 0
DSS Import GetPeak= 0
DSS Import FillOption= 0

--- ROARCKT3.g01 (geometry) ---

Geom Title=Geometry
Program Version=6.20

River Reach=ROARCKT3        ,Main
Reach XY= 30
2259429.22479565691725.1859393422259515.22832936691742.832760274
2259608.15500003691786.9920000142259734.18700001691812.561000019
2259835.22899999691879.2280000152259905.54099999691914.643999994
2260048.77000003      692026.1032260330.54100002692295.373999998
     2260457.561692398.9689999972260562.46000002692455.232000008
     2260663.354692457.8740000132260806.58300003692472.457000002
      2260905.02692503.1860000042260933.14500003692503.707000017
2260961.52800003692496.4170000112261022.72900002692447.978000015
2261121.68700002692417.2489999982261190.95800003692412.040000007
2261224.29099998692421.9360000042261283.66599999692477.144999996
2261312.83300002692493.8110000042261360.22900002692503.186000004
2261409.70800002692503.1860000042261686.85600001692448.895999998
2261763.10600002      692516.9192261819.99100001692654.859999999
     2261856.583692714.1240000132261906.85800001692818.188999996
2261941.47900003692830.7900000212262015.09364592692839.185896495

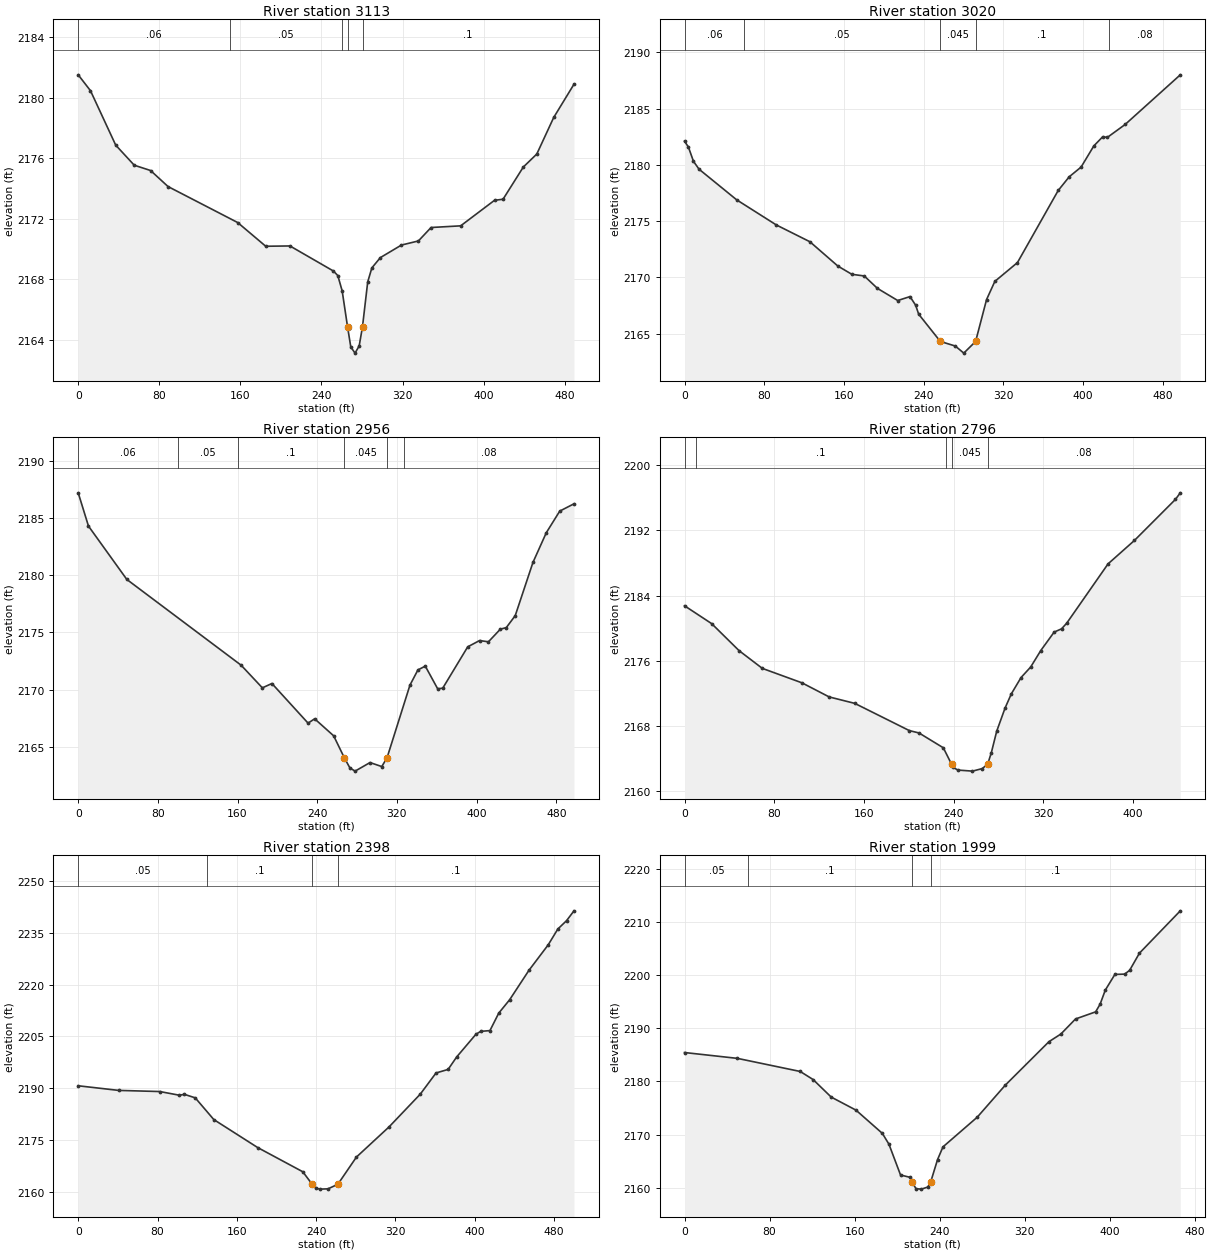
Type RM Length L Ch R = 1 ,3113    ,81.5,92.5,96.4
XS GIS Cut Line= 3
2259330.97452108691979.6678676252259427.64072257691732.718617964
2259491.18595646691517.993494654
#Sta/Elev= 30
       0 2181.52    12.1 2180.47      37 2176.87    55.3 2175.54    71.4 2175.19
    88.6 2174.13   157.3 2171.75     185 2170.18   208.9  2170.2   251.8 2168.54
   256.1 2168.24   260.4 2167.23  265.692164.861   268.9 2163.52   273.1 2163.11
   277.2 2163.59  280.462164.863   285.6 2167.82   289.7 2168.75   298.1 2169.43
   318.9 2170.26   335.6 2170.53   348.1 2171.42   377.3 2171.53   410.7 2173.22
   419.1 2173.29   439.1 2175.42   452.4 2176.28   469.1  2178.7   489.1  2180.9
#Mann= 5 ,-1,0
       0     .06       0     150     .05       0     260      .1       0
  265.69    .045       0  280.46      .1       0
Bank Sta=265.69,280.46
XS Rating Curve= 0 ,0
Exp/Cntr(USF)=0,0
Exp/Cntr=0.3,0.1

Type RM Length L Ch R = 1 ,3020    ,64.1,64.1,66.5
XS GIS Cut Line= 4
2259380.35627714691988.7007147132259463.70167861 691810.19228021
2259573.17026562691681.4422943492259632.26268937691563.638825911
#Sta/Elev= 30
       0  2182.1     3.9 2181.58       9 2180.31    14.6 2179.61    52.4 2176.89
    92.2 2174.66   125.9 2173.17     154 2171.01     168 2170.28   180.5 2170.13
   193.7 2169.03   214.1 2167.95   226.4  2168.3   232.1 2167.53   235.1 2166.74
  256.862164.318   271.9 2163.91   280.4 2163.28  292.282164.317   303.3 2168.04
   311.6 2169.65   334.3 2171.32   375.2 2177.72   386.3 2178.94   398.2  2179.8
     411 2181.68     420  2182.5   424.5 2182.43   442.4 2183.58   497.8 2187.99
#Mann= 5 ,-1,0
       0     .06       0      60     .05       0  256.86    .045       0
  292.28      .1       0     426     .08       0
Bank Sta=256.86,292.28
XS Rating Curve= 0 ,0
Exp/Cntr(USF)=0,0
Exp/Cntr=0.3,0.1

Type RM Length L Ch R = 1 ,2956    ,168.4,160.4,153.7
XS GIS Cut Line= 4
2259430.67272324692025.4280476362259514.01812472691846.919613133
2259623.48671173691718.1696272722259682.57913547691600.366158834
#Sta/Elev= 30
       0 2187.22    10.3 2184.31    48.8 2179.64   163.6 2172.13   184.9 2170.15
   194.5 2170.53   230.8 2167.06   237.4 2167.44   256.5 2165.95  267.192164.031
   272.8 2163.14     278 2162.86     293 2163.61   304.8 2163.26   310.1 2164.03
   333.1 2170.39   341.1 2171.72   348.5 2172.05   360.9 2170.07     366 2170.12
   391.1 2173.74     403 2174.29   411.9 2174.18   423.9 2175.29   429.8 2175.42
   438.8 2176.47   456.6 2181.13     470 2183.73   483.5 2185.62   497.8 2186.26
#Mann= 6 ,-1,0
       0     .06       0     100     .05       0     160      .1       0
  267.19    .045       0   310.1      .1       0  327.01     .08       0
Bank Sta=267.19,310.1
XS Rating Curve= 0 ,0
Exp/Cntr(USF)=0,0
Exp/Cntr=0.3,0.1

Type RM Length L Ch R = 1 ,2796    ,392.9,398.5,401.8
XS GIS Cut Line= 4
2259615.23671565692042.3831908132259698.21433955691890.562097105
2259751.42823602691762.0194381132259816.33965634691649.455862382
#Sta/Elev= 30
       0 2182.76    24.2 2180.57    48.7 2177.25    69.4 2175.08   104.7 2173.31
     129 2171.58   151.8 2170.79   200.5 2167.45   209.1 2167.16   230.8 2165.34
   238.2 2163.31   239.5 2162.94   243.8 2162.61   256.8 2162.48   265.4 2162.79
  270.292163.312   273.6 2164.74   278.4 2167.38   285.8  2170.2   291.4 2171.95
   300.1 2173.96   308.7 2175.25   317.7 2177.27   329.6 2179.53   336.2 2179.93
   340.8 2180.62   377.7  2187.9   401.2 2190.77   437.8 2195.81   442.1 2196.61
#Mann= 5 ,-1,0
       0     .05       0      10      .1       0  233.02     .08       0
   238.2    .045       0  270.29     .08       0
Bank Sta=238.2,270.29
XS Rating Curve= 0 ,0
Exp/Cntr(USF)=0,0
Exp/Cntr=0.3,0.1

Type RM Length L Ch R = 1 ,2398    ,398.2,398.3,398.2
XS GIS Cut Line= 4
2259909.51241134 692235.535910612260037.26949277692061.253074351
2260088.20970457691999.6769941562260204.46354037691831.798580795
#Sta/Elev= 30
       0 2190.65    40.8 2189.31    82.3 2188.98   102.1 2187.91   107.1 2188.17
   118.1 2187.15   136.8 2180.86     181 2172.76   226.6 2165.73  236.032162.111
   239.5 2161.04   243.8  2160.7     252 2160.78  261.98 2162.11   280.7 2169.99
   313.6 2178.73   345.1 2188.22     361 2194.36   373.2 2195.39   381.8 2198.99
   401.3 2205.59   406.1 2206.42   415.4 2206.64   424.3 2211.71   435.3 2215.59
   454.7 2224.09   474.2  2231.5   483.9 2236.08   492.7  2238.5   500.2 2241.35
#Mann= 4 ,-1,0
       0     .05       0     130      .1       0  236.03    .045       0
  261.98      .1       0
Bank Sta=236.03,261.98
XS Rating Curve= 0 ,0
Exp/Cntr(USF)=0,0
Exp/Cntr=0.3,0.1

Type RM Length L Ch R = 1 ,1999    ,391.7,387.8,383.1
XS GIS Cut Line= 4
2260197.33636819692473.281857673 2260323.3970696692340.189700372
2260359.53118899692293.9491561892260471.68205209692099.908303411
#Sta/Elev= 30
       0 2185.45    49.7 2184.35   108.8 2181.88   120.9 2180.36   137.9 2177.06
   161.2  2174.6     186 2170.22   192.2 2168.18   203.1 2162.38   211.7 2161.96
  213.862161.129   217.6  2159.8   222.7 2159.72   228.8 2160.12  231.532161.129
   237.9 2165.29     243 2167.68   275.2 2173.27   301.6 2179.31   342.6 2187.49
   353.8 2188.93   367.6 2191.77   386.5 2193.11   390.7 2194.55   395.6 2197.21
   404.6 2200.16   413.8 2200.22   418.5 2200.94   427.7 2204.17   466.1 2212.14
#Mann= 4 ,-1,0
       0     .05       0      60      .1       0  213.86    .045       0
  231.53      .1       0
Bank Sta=213.86,231.53
XS Rating Curve= 0 ,0
Exp/Cntr(USF)=0,0
Exp/Cntr=0.3,0.1

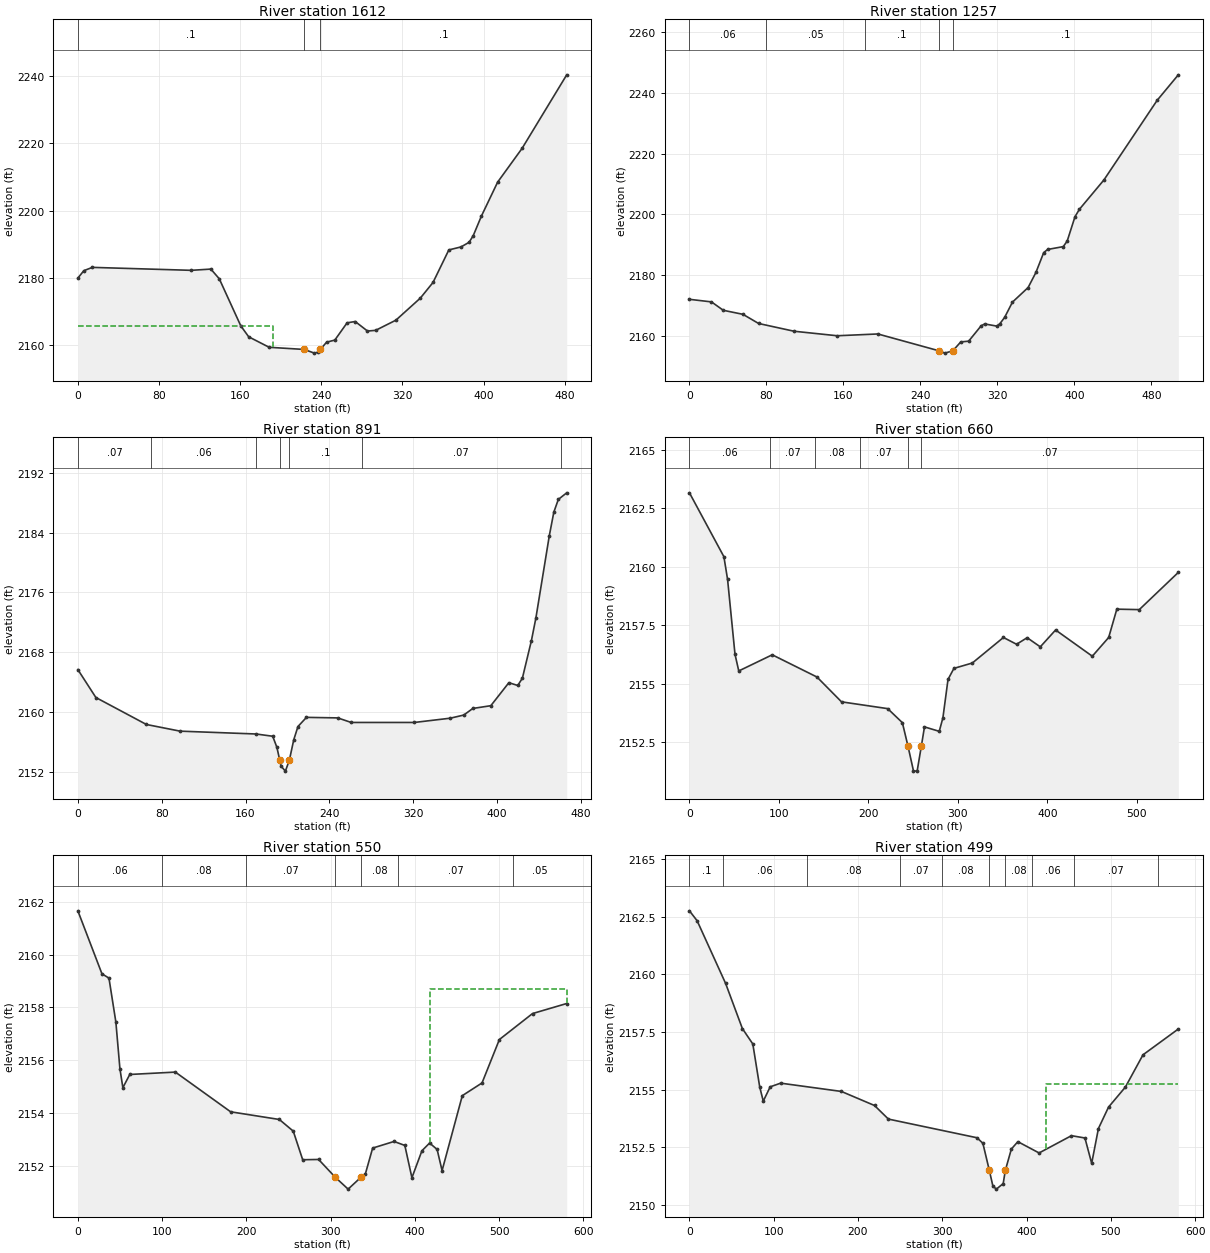
Type RM Length L Ch R = 1 ,1612    ,356.1,354.1,350
XS GIS Cut Line= 4
2260632.50828982692682.8560357162260678.04248719692528.814643253
2260693.24645761692428.1304956952260709.36475068692209.303181079
#Sta/Elev= 30
       0 2179.84     5.9 2182.06    14.3 2183.04   111.7 2182.16   131.1 2182.53
   139.4 2179.64   160.6  2165.6   168.4 2162.33   188.6  2159.2  223.252158.555
   233.1 2157.46   237.1 2157.78  239.022158.556   245.2 2160.73   253.3 2161.35
   265.4  2166.5   273.4 2166.89   285.5 2164.05   293.5 2164.25   313.5 2167.29
   337.6 2173.87   350.1 2178.54   365.7 2188.25   377.7 2189.14   385.7 2190.53
   389.8 2192.54   397.8 2198.34   413.8 2208.47   437.9 2218.54   481.9 2240.48
#Mann= 3 ,-1,0
       0      .1       0  223.25    .045       0  239.02      .1       0
#XS Ineff= 2 , 0
          192.06  2165.6
Permanent Ineff=
       F       F
Bank Sta=223.25,239.02
XS Rating Curve= 0 ,0
Exp/Cntr(USF)=0,0
Exp/Cntr=0.3,0.1

Type RM Length L Ch R = 1 ,1257    ,364,366.1,369.5
XS GIS Cut Line= 4
2261013.23519936692707.6465950342261045.82557344692548.312912428
 2261003.2510736692393.4876298662260970.46469646692211.565504915
#Sta/Elev= 30
       0    2172    22.9 2171.15    35.2 2168.38    55.6 2167.06    71.9 2164.04
   108.7 2161.49   153.6    2160   195.8 2160.59  259.522155.032   265.4 2154.28
   273.7 2155.03     282 2157.97   290.2 2158.22   303.2 2163.29   306.9 2163.89
   319.4 2163.18   322.7 2163.99   327.6 2166.05   335.7 2171.07     352 2175.88
   360.1 2180.84   368.2 2187.38   372.3 2188.42   388.5 2189.35   392.6 2191.17
   400.7 2199.19   405.3 2201.64   430.8 2211.31   486.1 2237.52   508.1 2245.92
#Mann= 5 ,-1,0
       0     .06       0      80     .05       0  182.63      .1       0
  259.52    .045       0   273.7      .1       0
Bank Sta=259.52,273.7
XS Rating Curve= 0 ,0
Exp/Cntr(USF)=0,0
Exp/Cntr=0.3,0.1

Type RM Length L Ch R = 1 ,891     ,232.7,231.1,229.2
XS GIS Cut Line= 3
2261332.15160529692698.2809904272261352.72962102692478.580410686
2261263.15472901692249.801294593
#Sta/Elev= 30
       0 2165.69    17.2 2161.96    65.4 2158.36    97.5 2157.47     170 2157.09
   185.9 2156.79   189.9  2155.3  192.64 2153.58   193.9 2152.79     198 2152.13
   201.82153.603     206 2156.33     210 2158.09   218.1 2159.31   247.9 2159.24
   260.8 2158.63     321 2158.63   355.3  2159.2   368.2 2159.62   376.8  2160.5
     394 2160.87   411.2 2163.94   419.7 2163.57   424.1 2164.54   432.7 2169.55
     437 2172.59   449.8 2183.58   454.1 2186.72   458.4 2188.42   466.4  2189.3
#Mann= 7 ,-1,0
       0     .07       0      70     .06       0     170      .1       0
  192.64    .045       0   201.8      .1       0  270.66     .07       0
  460.66      .1       0
Bank Sta=192.64,201.8
XS Rating Curve= 0 ,0
Exp/Cntr(USF)=0,0
Exp/Cntr=0.3,0.1

Type RM Length L Ch R = 1 ,660     ,80.7,110.1,111.9
XS GIS Cut Line= 4
2261527.06884537692714.1497303192261586.73714611692505.719531166
2261557.30914177692384.3113493452261459.29220823692204.917831413
#Sta/Elev= 30
       0 2163.16    38.5 2160.43    42.6 2159.46    50.9 2156.26    55.1 2155.55
    92.5 2156.24   142.5 2155.29   169.9 2154.23   221.5 2153.94   237.9 2153.34
  244.14 2152.34   250.3 2151.28   254.4 2151.27   259.1 2152.34   262.6 2153.16
   279.1 2152.97   283.2 2153.55   288.9 2155.19   295.5 2155.66   316.1 2155.89
   350.8 2156.98   365.5 2156.69   377.3 2156.97     392 2156.58   409.1  2157.3
   450.1 2156.18   468.4 2156.98   477.5 2158.19   502.6 2158.17   546.2 2159.76
#Mann= 6 ,-1,0
       0     .06       0      90     .07       0     140     .08       0
     190     .07       0  244.14    .045       0   259.1     .07       0
Bank Sta=244.14,259.1
XS Rating Curve= 0 ,0
Exp/Cntr(USF)=0,0
Exp/Cntr=0.3,0.1

Type RM Length L Ch R = 1 ,550     ,63,50.9,54.9
XS GIS Cut Line= 6
2261551.21324805 692724.923979712261615.32855967692472.955349524
2261680.97208437692450.321795363 2261744.7037511692427.892797387
2261772.65411498692419.0119205932261772.94363185692265.241289451
#Sta/Elev= 30
       0 2161.65    28.6 2159.27    36.9 2159.11    45.1 2157.45    49.9 2155.69
    53.4 2154.97    61.6 2155.47   115.7 2155.56   181.3 2154.06   239.1 2153.77
   255.6 2153.33   266.8 2152.25   285.7 2152.26  305.272151.594   320.7 2151.14
     336 2151.59   341.3 2151.73   349.8 2152.69   375.2 2152.94     388 2152.79
   396.4 2151.57   408.3 2152.59   417.4 2152.88   426.3 2152.64   432.2 2151.84
   456.2 2154.67   479.6 2155.15   500.2 2156.79   539.5 2157.77   580.1 2158.15
#Mann= 7 ,-1,0
       0     .06       0     100     .08       0     200     .07       0
  305.27    .045       0     336     .08       0     380     .07       0
  516.32     .05       0
#XS Ineff= 2 , 0
                          417.84         2158.68
Permanent Ineff=
       F       F
Bank Sta=305.27,336
XS Rating Curve= 0 ,0
Exp/Cntr(USF)=0,0
Exp/Cntr=0.3,0.1

Type RM Length L Ch R = 1 ,499     ,110.2,110,108.3
XS GIS Cut Line= 6
2261561.58613166692766.0313332912261625.70144328692514.062703104
2261691.34496798692491.4291489442261755.07663471692469.000150967
 2261783.0269986692460.1192741732261783.31651546692306.348643032
#Sta/Elev= 30
       0 2162.76     9.1 2162.33    42.9 2159.61    62.8 2157.65    75.2 2156.98
    83.4 2155.11    87.6  2154.5    95.8 2155.12   108.2 2155.28   180.3 2154.92
   219.6 2154.31   236.1 2153.72   341.2 2152.91   348.2 2152.67   355.8  2151.5
   360.1 2150.81   364.2 2150.68   372.3 2150.92  374.862151.498     382 2152.42
   389.7 2152.74   414.9 2152.25   453.3    2153   469.3  2152.9   477.3  2151.8
   485.3 2153.31   497.3 2154.24   517.3 2155.11   538.2 2156.51   580.1 2157.63
#Mann= 10 ,-1,0
       0      .1       0      40     .06       0     140     .08       0
     250     .07       0     300     .08       0   355.8    .045       0
  374.86     .08       0     407     .06       0  456.32     .07       0
  556.32     .05       0
#XS Ineff= 2 , 0
                          423.15         2155.24
Permanent Ineff=
       F       F
Bank Sta=355.8,374.86
XS Rating Curve= 0 ,0
Exp/Cntr(USF)=0,0
Exp/Cntr=0.3,0.1

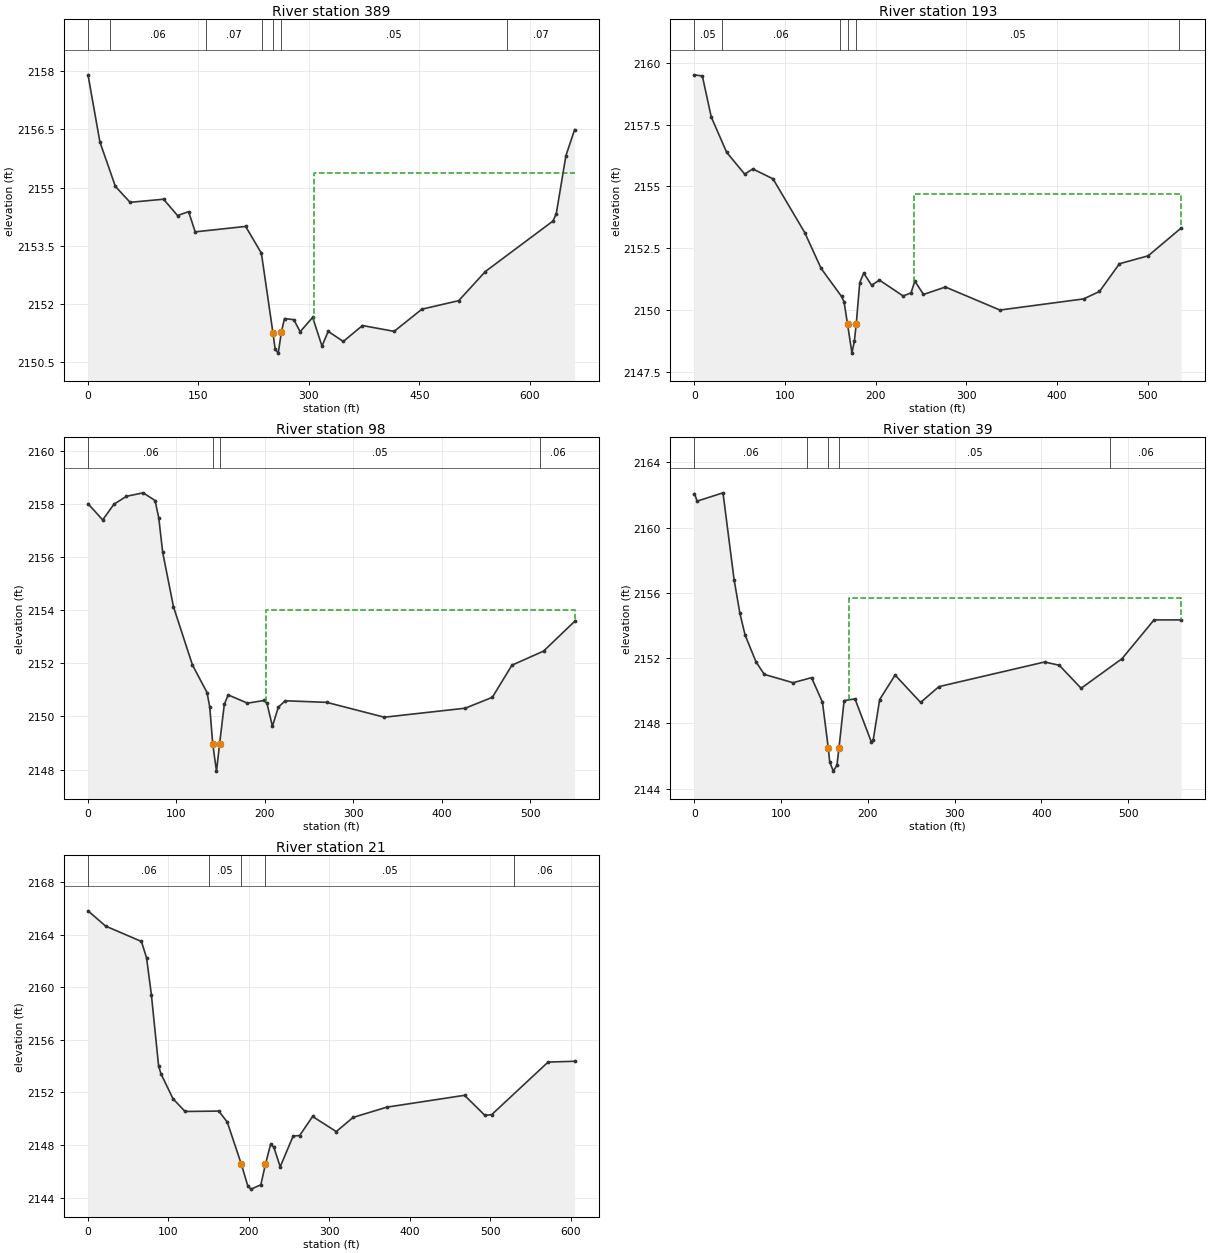
Type RM Length L Ch R = 1 ,389     ,197.4,196.5,196.6
XS GIS Cut Line= 4
2261603.44229531692749.257273889 2261753.5429367692580.306713747
2262011.57359881692490.1474858882262076.89447464692342.334347253
#Sta/Elev= 30
       0  2157.9    16.2 2156.17    37.2 2155.03    57.2 2154.62   102.6  2154.7
   121.6 2154.28   136.6 2154.38   145.6 2153.86   214.1    2154   235.5 2153.31
251.2752 2151.25   254.2 2150.84   258.4 2150.74262.67512151.287   266.9 2151.63
   279.6  2151.6   288.1 2151.29   305.1 2151.66   317.8 2150.92   326.2  2151.3
   346.7 2151.04   372.8 2151.45   415.8  2151.3   453.4 2151.87   503.5 2152.09
   539.7 2152.84   631.6 2154.14     636 2154.33   649.1 2155.82   660.9 2156.49
#Mann= 7 ,-1,0
       0      .1       0      30     .06       0     160     .07       0
     236     .05       0251.2752    .045       0262.6751     .05       0
  569.33     .07       0
#XS Ineff= 2 , 0
                          307.29         2155.37
Permanent Ineff=
       F       F
Bank Sta=251.2752,262.6751
XS Rating Curve= 0 ,0
Exp/Cntr(USF)=0,0
Exp/Cntr=0.3,0.1

Type RM Length L Ch R = 1 ,193     ,97.8,94.3,91.9
XS GIS Cut Line= 4
 2261742.5432826692853.6139182632261814.38126453692769.068610556
2261937.70091055692717.1300813232262058.23652277692451.280378182
#Sta/Elev= 30
       0 2159.51     8.7 2159.46    18.5 2157.81    35.5 2156.38    55.4  2155.5
    64.3 2155.71    86.6 2155.31   121.6 2153.14   139.7 2151.69   162.2 2150.56
     165 2150.34  168.832149.441   173.7 2148.27   176.4 2148.77  178.382149.427
   182.3 2151.12   186.7  2151.5   195.4 2151.01     204 2151.22   230.1 2150.58
   238.8  2150.7   243.1 2151.18   252.6 2150.64   276.8 2150.94   336.9 2150.01
   429.2 2150.46   446.7 2150.76   468.7 2151.88   500.4  2152.2   536.7 2153.32
#Mann= 6 ,-1,0
       0     .05       0      30     .06       0  160.94     .05       0
  168.83    .045       0  178.38     .05       0  534.76     .06       0
#XS Ineff= 2 , 0
                           242.6         2154.71
Permanent Ineff=
       F       F
Bank Sta=168.83,178.38
XS Rating Curve= 0 ,0
Exp/Cntr(USF)=0,0
Exp/Cntr=0.3,0.1

Type RM Length L Ch R = 1 ,98      ,60.5,59.7,60.3
XS GIS Cut Line= 6
2261784.49191419692876.6663767932261914.68154321692832.170594396
2261930.63563305692796.162870198 2261947.3872956692752.001419484
2261955.29992036692726.1235565212262072.56230818692451.487627537
#Sta/Elev= 30
       0 2158.01    16.6  2157.4    29.3 2157.99    43.5 2158.29    62.4 2158.42
    75.8 2158.13      80 2157.47    84.4 2156.18    96.6 2154.13     118 2151.94
   134.5  2150.9   137.6 2150.35     141 2148.95   145.2 2147.94  148.652148.947
     154 2150.45   158.4 2150.81   180.2  2150.5   199.1  2150.6   202.2  2150.5
   208.4 2149.63   215.1 2150.35   222.9 2150.59   269.7 2150.53   334.9 2149.97
   426.3 2150.31   456.9 2150.72   479.1 2151.93   514.8 2152.46   549.9 2153.58
#Mann= 4 ,-1,0
       0     .06       0     141    .045       0  148.65     .05       0
  511.26     .06       0
#XS Ineff= 2 , 0
                          201.01         2153.99
Permanent Ineff=
       F       F
Bank Sta=141,148.65
XS Rating Curve= 0 ,0
Exp/Cntr(USF)=0,0
Exp/Cntr=0.3,0.1

Type RM Length L Ch R = 1 ,39      ,22.8,18.2,17.5
XS GIS Cut Line= 4
 2261841.2436032692901.2990843042261971.15334094692854.284280445
2261982.50950953692814.744107395 2262100.4321196692451.541038445
#Sta/Elev= 30
       0 2162.08     3.1 2161.62    32.9 2162.13    45.7 2156.81    52.4 2154.74
    58.4 2153.41    70.9 2151.78    80.5    2151   113.7 2150.49     135  2150.8
   147.6  2149.3  154.342146.484     156 2145.63   160.1 2145.07   164.3 2145.43
  166.65 2146.48   172.6 2149.39   185.1  2149.5   204.1 2146.84   206.2    2147
   213.6 2149.46   231.4 2150.96   260.8 2149.28   281.9 2150.25   403.8 2151.76
   420.7 2151.56   445.9 2150.15     493 2151.96     530 2154.34   561.2 2154.34
#Mann= 5 ,-1,0
       0     .06       0     130     .05       0  154.34    .045       0
  166.65     .05       0  479.29     .06       0
#XS Ineff= 2 , 0
                          178.48         2155.69
Permanent Ineff=
       F       F
Bank Sta=154.34,166.65
XS Rating Curve= 0 ,0
Exp/Cntr(USF)=0,0
Exp/Cntr=0.3,0.1

Type RM Length L Ch R = 1 ,21      ,,,
XS GIS Cut Line= 4
2261824.45497438692938.8384586342261992.53478204 692856.93154729
 2262002.6093516 692764.53698102 2262102.2744092692455.033668538
#Sta/Elev= 30
       0 2165.82    21.9 2164.66    66.4 2163.49    72.8 2162.25    78.8 2159.45
    87.8 2154.01    90.8 2153.41   105.7 2151.52   120.7 2150.55   162.6 2150.58
   173.2 2149.74   190.62146.552   198.8 2144.87   202.8 2144.64   214.9 2144.97
   220.6 2146.52     227 2148.04     231 2147.85     239 2146.34   255.1 2148.68
   263.2 2148.72   279.3 2150.17   308.7 2149.02   329.7  2150.1   371.7 2150.88
   468.2 2151.78   493.6 2150.25     502 2150.31   572.1 2154.31   605.1 2154.37
#Mann= 5 ,-1,0
       0     .06       0     150     .05       0   190.6    .045       0
   220.6     .05       0  529.92     .06       0
Bank Sta=190.6,220.6
XS Rating Curve= 0 ,0
Exp/Cntr(USF)=0,0
Exp/Cntr=0.3,0.1
LCMann Table=0

Chan Stop Cuts=-1
Use User Specified Reach Order=0
Composite Channel Slope=5